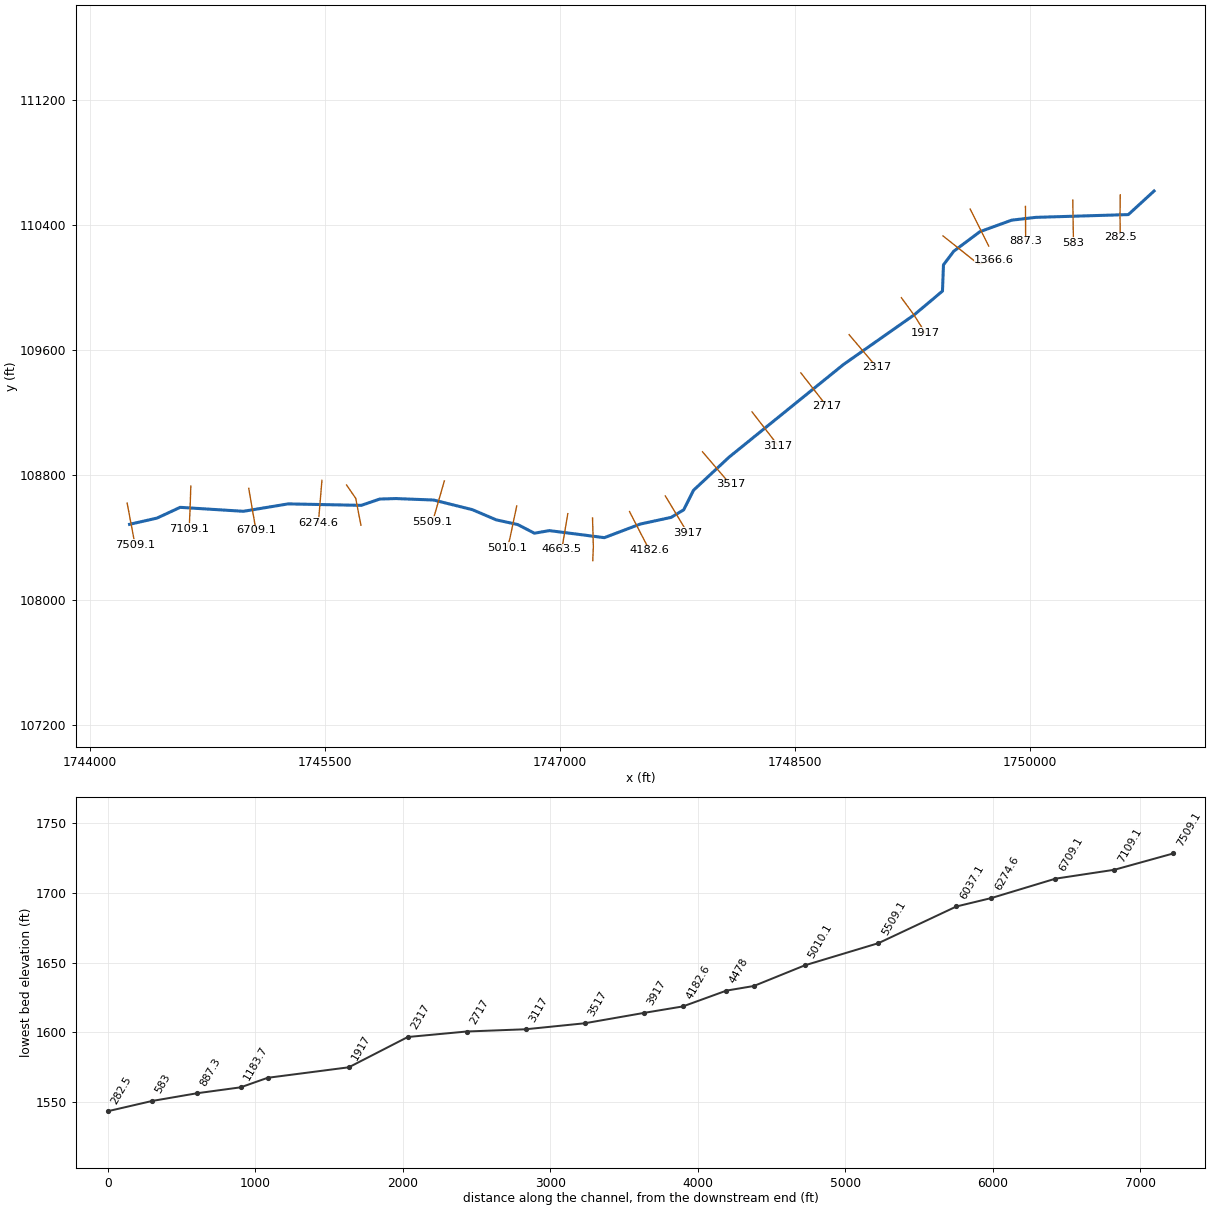
--- Mudlick Branch.prj (project) ---

Proj Title=Mudlick Branch
Current Plan=p01
Default Exp/Contr=0,0
English Units
Geom File=g01
Flow File=f01
Plan File=p01
BEGIN DESCRIPTION:
END DESCRIPTION:
DSS Export Rating Curves= 0
DSS Export Rating Curve Sorted= 0
DSS Export Volume Flow Curves= 0
DXF OffsetX= 0
DXF OffsetY= 0
DXF ScaleX= 0
DXF ScaleY= 0

--- Mudlick Branch.p01 (plan) ---

Plan Title=Floodplain
Program Version=4.00
Geom File=g01
Flow File=f01
K Sum by GR=0
Std Step Tol=0.01
Critical Tol=0.01
Num of Std Step Trials=20
Max Error Tol=0.3
Flow Tol Ratio=0.001
Split Flow NTrial=30
Split Flow Tol=0.02
Split Flow Ratio=0.02
Log Output Level=0
Friction Slope Method=1
Unsteady Friction Slope Method=2
Unsteady Bridges Friction Slope Method=1
Global Log Level=0
CheckData=False
Run HTab=0
Run UNet=0
Run PostProcess=0
UNET Theta=0
UNET Theta Warmup=0
UNET ZTol=0
UNET ZSATol=0
UNET MxIter=0
UNET MaxInSteps=0
UNET DtIC=0
UNET DtMin=0
UNET MaxCRTS=0
UNET WFStab=0
UNET SFStab=0
UNET WFX=0
UNET SFX=0
UNET DSS MLevel=0
UNET DZMax Abort=0
UNET Convert EG Bridges=0
UNET Use Existing IB Tables=0
UNET Froude Limit=0
UNET Froude Power=0
Write IC File=0
Echo Input=False
Echo Output=False
Write Detailed=0

--- Mudlick Branch.f01 (steady flow) ---

Flow Title=NFF Regression Equation
Program Version=4.00
Number of Profiles=1
Profile Names=P100yr
River Rch & RM=Mudlick Branch,Main      ,7509.1
584.1629
River Rch & RM=Mudlick Branch,Main      ,6274.6
602.3699
River Rch & RM=Mudlick Branch,Main      ,4478
667.4962
River Rch & RM=Mudlick Branch,Main      ,4182.6
1081.713
River Rch & RM=Mudlick Branch,Main      ,1183.7
1135.589
River Rch & RM=Mudlick Branch,Main      ,282.5
1259.677
Boundary for River Rch & Prof#=Mudlick Branch,Main      ,1
Up Type=0
Dn Type=3
Dn Slope=0.018866

--- Mudlick Branch.g01 (geometry) ---

Geom Title=Geometry
Program Version=4.00

River Reach=Mudlick Branch  ,Main
Reach XY= 30
     1744251.114      108481.802     1744426.216      108521.573
     1744574.295      108590.465     1744978.145      108565.125
     1745264.009      108612.637     1745731.209      108603.135
     1745848.405       108643.52     1745952.139      108646.687
     1746193.658      108637.185      1746440.72      108575.419
     1746592.758      108510.487     1746729.751      108480.396
     1746836.653      108424.965     1746931.943      108441.611
     1747283.219      108396.419     1747512.905      108483.563
     1747710.079      108526.324     1747790.058      108574.628
     1747852.615      108699.742     1748078.296      108910.378
      1748809.98      109504.277     1749261.343      109821.815
      1749442.68      109974.645     1749449.015       110142.52
     1749514.739      110229.625     1749681.823       110354.74
      1749884.54      110428.383     1750039.557      110446.384
     1750629.685      110464.017     1750793.964      110615.006

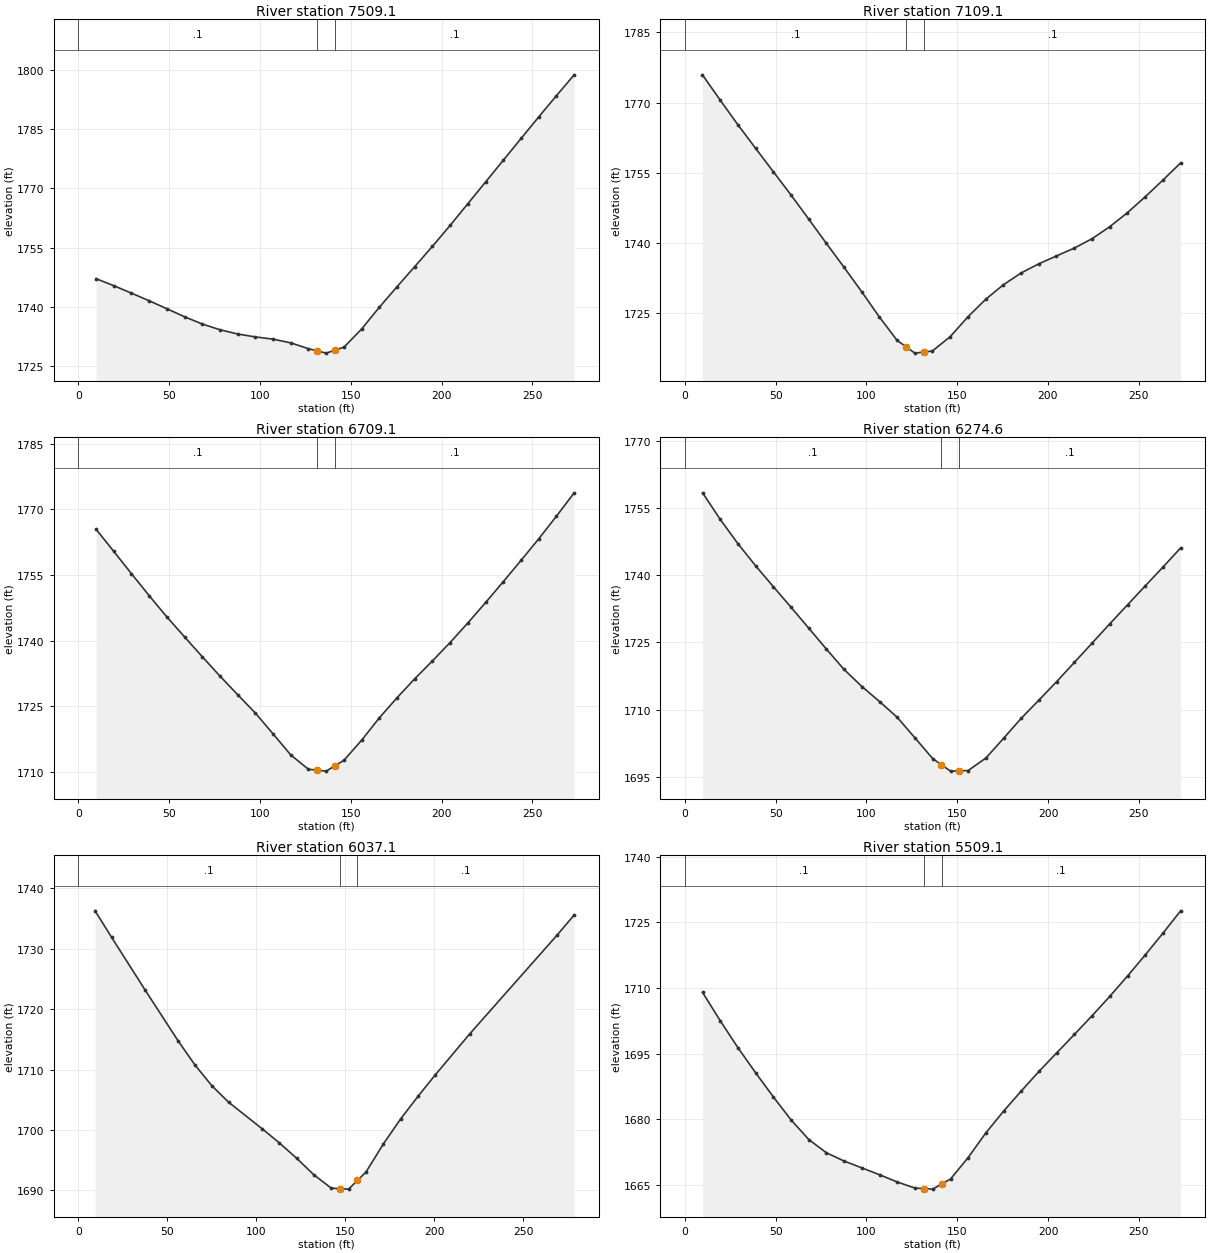
Type RM Length L Ch R = 1 ,7509.1  ,404.6,400,395.2
XS GIS Cut Line= 3
     1744235.605      108617.786      1744260.94      108483.658
     1744286.276       108349.53
#Sta/Elev= 30
     9.8 1747.11    19.5 1745.34    29.2 1743.46      39 1741.51    48.8 1739.48
    58.5 1737.45    68.2 1735.62      78 1734.16    87.7 1733.08    97.5 1732.34
   107.3 1731.77     117 1730.83   126.7 1729.35   131.5  1728.8   136.5 1728.23
   141.5 1729.01   146.3 1729.76     156 1734.35   165.7 1739.85   175.5 1745.09
   185.2 1750.17     195 1755.34   204.8 1760.68   214.5 1766.16   224.2 1771.63
     234 1777.17   243.8  1782.7   253.5 1788.15   263.2 1793.51     273 1798.83
#Mann= 3 , 0 , 0
       0      .1       0   131.5    .045       0   141.5      .1       0
Bank Sta=131.5,141.5
XS Rating Curve= 0 ,0
Exp/Cntr=0.3,0.1

Type RM Length L Ch R = 1 ,7109.1  ,395.9,400,404.3
XS GIS Cut Line= 3
     1744642.336      108726.792     1744637.873      108590.465
     1744631.992      108453.925
#Sta/Elev= 30
     9.7 1775.93    19.5 1770.53    29.2  1765.3      39 1760.24    48.7 1755.28
    58.5 1750.28    68.2 1745.16    77.9 1739.99    87.7 1734.85    97.4 1729.65
   107.2 1724.22   116.9 1719.26   121.7 1717.92   126.7 1716.52   131.7 1716.76
   136.4 1716.98   146.2 1720.04   155.9 1724.25   165.7    1728   175.4 1731.09
   185.2 1733.62     195 1735.59   204.7 1737.26   214.5 1738.94   224.3 1740.94
     234 1743.49   243.8  1746.5   253.5 1749.86   263.3 1753.44   273.1 1757.13
#Mann= 3 , 0 , 0
       0      .1       0   121.7    .045       0   131.7      .1       0
Bank Sta=121.7,131.7
XS Rating Curve= 0 ,0
Exp/Cntr=0.3,0.1

Type RM Length L Ch R = 1 ,6709.1  ,439.6,434.5,429.4
XS GIS Cut Line= 3
     1745012.101      108712.189     1745035.245      108577.665
     1745058.389      108443.141
#Sta/Elev= 30
     9.8 1765.45    19.5 1760.41    29.2 1755.33      39 1750.28    48.7 1745.43
    58.5 1740.84    68.2 1736.32      78 1731.87    87.8 1727.59    97.5  1723.4
   107.2 1718.67     117 1713.82   126.7 1710.55   131.5 1710.35   136.5 1710.13
   141.5 1711.41   146.3 1712.63     156 1717.21   165.7  1722.3   175.5 1726.93
   185.2 1731.25     195 1735.36   204.7 1739.55   214.5 1744.04   224.3 1748.73
     234 1753.48   243.7 1758.32   253.5 1763.28   263.2 1768.43     273  1773.8
#Mann= 3 , 0 , 0
       0      .1       0   131.5    .045       0   141.5      .1       0
Bank Sta=131.5,141.5
XS Rating Curve= 0 ,0
Exp/Cntr=0.3,0.1

Type RM Length L Ch R = 1 ,6274.6  ,231.9,237.5,243
XS GIS Cut Line= 3
     1745479.616      108762.948     1745468.281      108626.919
     1745456.945      108490.891
#Sta/Elev= 30
     9.8 1758.35    19.5 1752.43    29.2 1747.03      39 1742.07    48.8 1737.39
    58.5 1732.82    68.2 1728.18      78 1723.47    87.7 1718.94    97.5 1715.14
   107.3 1711.76     117 1708.25   126.7 1703.69   136.5 1699.05   141.2 1697.71
   146.3 1696.26   151.2 1696.32     156 1696.39   165.8 1699.19   175.5 1703.57
   185.2 1708.03     195 1712.12   204.8 1716.25   214.5 1720.52   224.3 1724.84
     234 1729.13   243.8 1733.37   253.5 1737.58   263.3 1741.79     273 1746.06
#Mann= 3 , 0 , 0
       0      .1       0   141.2    .045       0   151.2      .1       0
Bank Sta=141.2,151.2
XS Rating Curve= 0 ,0
Exp/Cntr=0.3,0.1

Type RM Length L Ch R = 1 ,6037.1  ,537.6,528.1,518.5
XS GIS Cut Line= 3
     1745637.053      108733.299     1745695.326      108648.242
     1745728.782      108476.072
#Sta/Elev= 23
     9.4 1736.28    18.7 1731.89    37.5 1723.17    56.2 1714.68    65.6 1710.72
      75 1707.32    84.4 1704.59   103.1 1700.23   112.8 1697.88   122.6 1695.32
   132.3 1692.57   142.1 1690.36   146.8 1690.28   151.8  1690.2   156.8 1691.65
   161.6 1693.04   171.3 1697.67   181.1 1701.85   190.8 1705.57   200.5 1709.12
     220 1715.96   268.8 1732.22   278.5 1735.59
#Mann= 3 , 0 , 0
       0      .1       0   146.8    .045       0   156.8      .1       0
Bank Sta=146.8,156.8
XS Rating Curve= 0 ,0
Exp/Cntr=0.3,0.1

Type RM Length L Ch R = 1 ,5509.1  ,497.5,499,500.6
XS GIS Cut Line= 3
      1746261.55      108759.654     1746223.666      108628.516
     1746185.782      108497.379
#Sta/Elev= 30
     9.8 1708.99    19.5 1702.51    29.2 1696.37      39 1690.59    48.8 1685.04
    58.5 1679.81    68.3 1675.29      78 1672.27    87.7 1670.38    97.5 1668.81
   107.3 1667.23     117 1665.58   126.7  1664.2   131.5 1664.08   136.5 1663.95
   141.5 1665.13   146.3 1666.26     156 1671.17   165.7  1676.8   175.5 1681.79
   185.3 1686.44     195  1690.9   204.8 1695.16   214.5 1699.36   224.2 1703.63
     234 1708.09   243.8 1712.76   253.5 1717.56   263.3 1722.57     273 1727.67
#Mann= 3 , 0 , 0
       0      .1       0   131.5    .045       0   141.5      .1       0
Bank Sta=131.5,141.5
XS Rating Curve= 0 ,0
Exp/Cntr=0.3,0.1

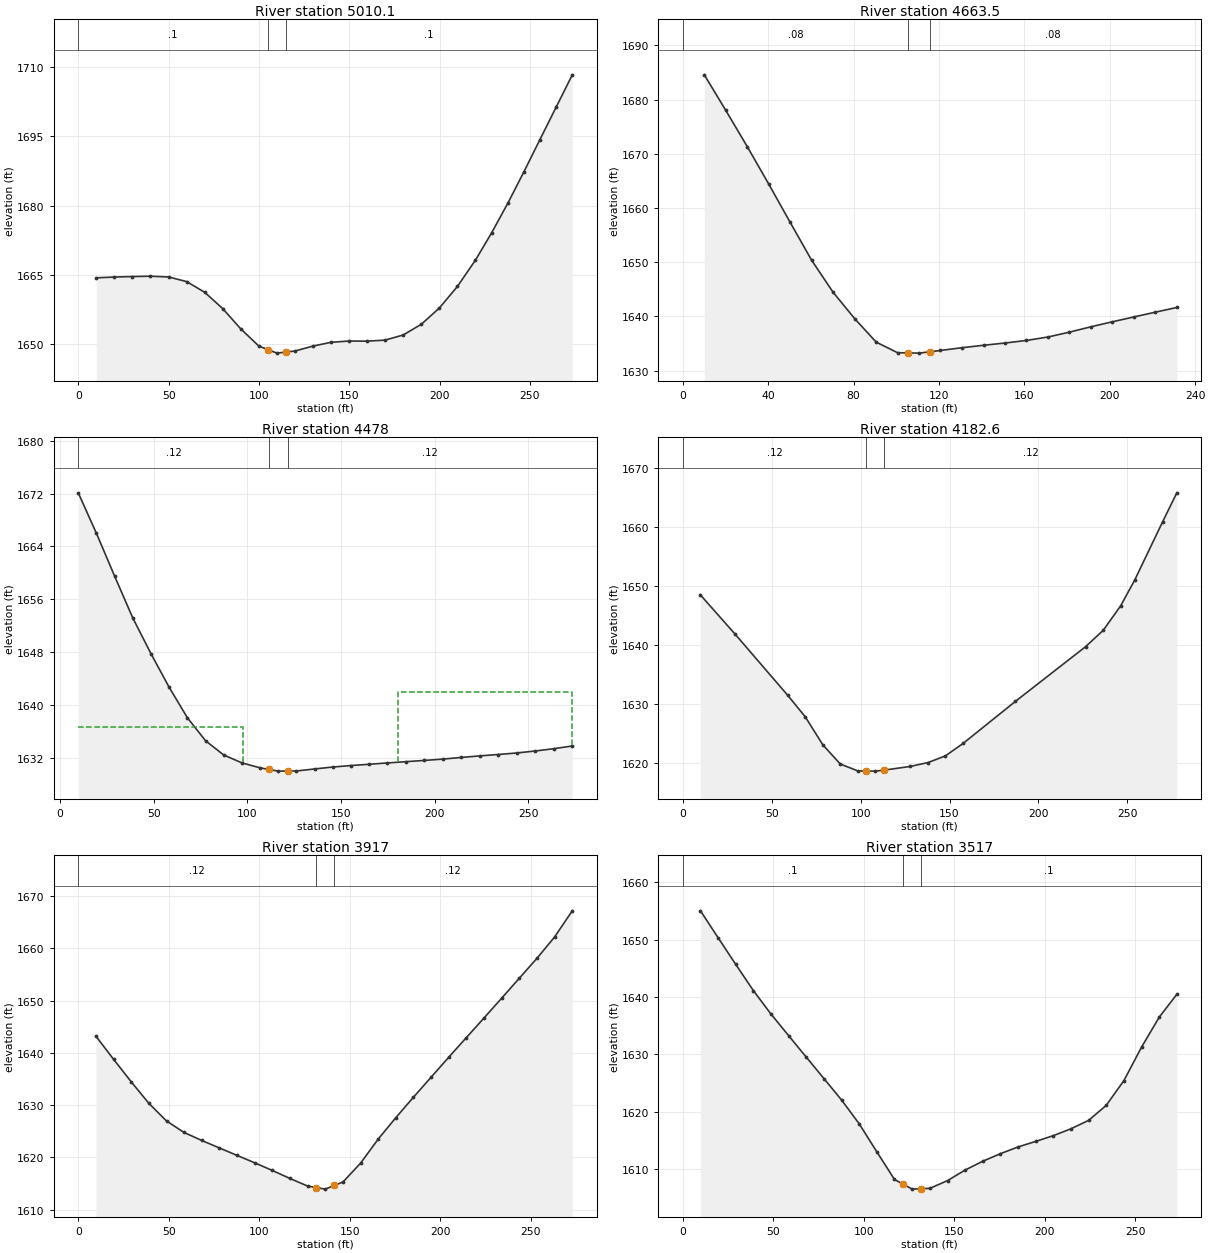
Type RM Length L Ch R = 1 ,5010.1  ,345.5,346.5,347.6
XS GIS Cut Line= 3
      1746723.57      108599.457     1746678.408      108384.229
     1746661.602      108333.334
#Sta/Elev= 30
      10 1664.37      20 1664.54      30 1664.65      40 1664.72      50 1664.56
      60 1663.56      70 1661.24      80  1657.7      90 1653.31     100 1649.59
     105 1648.83     110 1648.07     115  1648.3     120 1648.53   129.9 1649.59
   139.9 1650.41   149.9 1650.69   159.9 1650.66   169.9 1650.89   179.9    1652
   189.9 1654.31   199.9 1657.83   209.9  1662.5   219.9 1668.21   228.8 1674.08
   237.8 1680.51   246.7 1687.31   255.6 1694.31   264.6 1701.35   273.5 1708.32
#Mann= 3 , 0 , 0
       0      .1       0     105    .045       0     115      .1       0
Bank Sta=105,115
XS Rating Curve= 0 ,0
Exp/Cntr=0.3,0.1

Type RM Length L Ch R = 1 ,4663.5  ,181.6,185.5,189.4
XS GIS Cut Line= 2
     1747049.882      108550.066     1747011.408      108321.874
#Sta/Elev= 25
    10.1 1684.57    20.1 1678.05    30.2 1671.34    40.2 1664.47    50.3 1657.37
    60.4 1650.35    70.4 1644.48    80.5 1639.61    90.6 1635.27   100.6 1633.32
   105.7 1633.28   110.7 1633.24   115.7 1633.48   120.7 1633.73   130.8 1634.24
   140.9 1634.69   150.9  1635.1     161 1635.58     171 1636.21   181.1 1637.11
   191.2  1638.1   201.2 1639.02   211.3 1639.91   221.4  1640.8   231.4 1641.66
#Mann= 3 , 0 , 0
       0     .08       0   105.7    .045       0   115.7     .08       0
Bank Sta=105.7,115.7
XS Rating Curve= 0 ,0
Exp/Cntr=0.3,0.1

Type RM Length L Ch R = 1 ,4478    ,286.3,295.4,304.4
XS GIS Cut Line= 3
     1747207.759      108522.205     1747213.066      108337.795
     1747209.086      108248.906
#Sta/Elev= 30
     9.7 1672.12    19.4 1665.99    29.1 1659.51    38.8 1653.17    48.5 1647.76
    58.3 1642.62      68 1638.02    77.7 1634.54    87.4 1632.38    97.1 1631.19
   106.8 1630.44   111.5  1630.2   116.5 1629.94   121.5 1629.95   126.2 1629.96
   135.9 1630.27   145.6 1630.56   155.4 1630.79   165.1 1630.98   174.8 1631.18
   184.5 1631.37   194.4 1631.56   204.3 1631.76   214.1 1632.01     224 1632.25
   233.9 1632.46   243.8 1632.69   253.7 1632.99   263.6 1633.34   273.5 1633.75
#Mann= 3 , 0 , 0
     9.7     .12       0   111.5    .045       0   121.5     .12       0
#XS Ineff= 2 , 0
           97.65 1636.61   180.2         1641.92
Permanent Ineff=
       F       F
Bank Sta=111.5,121.5
XS Rating Curve= 0 ,0
Exp/Cntr=0.3,0.1

Type RM Length L Ch R = 1 ,4182.6  ,264.4,265.6,266.9
XS GIS Cut Line= 3
     1747443.911      108563.333      1747556.68      108344.428
      1747568.62      108315.241
#Sta/Elev= 21
     9.8 1648.49    29.5 1641.78    59.1 1631.42    68.9  1627.8    78.8 1623.05
    88.6 1619.81    98.5 1618.64   103.3 1618.62   108.3 1618.61   113.3 1618.78
     128 1619.41   137.9 1620.06   147.7 1621.19   157.6 1623.29   187.1 1630.43
   226.5 1639.68   236.4 1642.44   246.2 1646.58   254.1 1650.94   269.9 1660.87
   277.8 1665.73
#Mann= 3 , 0 , 0
       0     .12       0   103.3    .045       0   113.3     .12       0
Bank Sta=103.3,113.3
XS Rating Curve= 0 ,0
Exp/Cntr=0.3,0.1

Type RM Length L Ch R = 1 ,3917    ,396.6,400,403.4
XS GIS Cut Line= 3
     1747672.585      108663.143     1747743.154        108546.3
     1747813.722      108429.456
#Sta/Elev= 30
     9.8  1643.2    19.5  1638.8    29.3 1634.47      39 1630.37    48.8 1626.98
    58.5 1624.78    68.3 1623.25      78 1621.82    87.8 1620.39    97.5 1618.98
   107.2 1617.52     117 1615.98   126.7 1614.53   131.5 1614.24   136.5 1613.94
   141.5 1614.64   146.3 1615.31     156 1618.91   165.8 1623.54   175.5 1627.62
   185.2 1631.52     195 1635.37   204.7 1639.17   214.5 1642.96   224.3 1646.73
     234  1650.5   243.7  1654.3   253.5 1658.13   263.2  1662.2     273 1667.21
#Mann= 3 , 0 , 0
       0     .12       0   131.5    .045       0   141.5     .12       0
Bank Sta=131.5,141.5
XS Rating Curve= 0 ,0
Exp/Cntr=0.3,0.1

Type RM Length L Ch R = 1 ,3517    ,401,400,399
XS GIS Cut Line= 3
     1747909.935      108946.044     1747998.622      108842.281
     1748087.309      108738.517
#Sta/Elev= 30
     9.8 1655.02    19.5 1650.35    29.3 1645.68      39 1641.14    48.7 1637.06
    58.5 1633.28    68.2 1629.55      78 1625.81    87.8 1622.05    97.5 1617.92
   107.2 1613.06     117 1608.22   121.8  1607.4   126.8 1606.54   131.8 1606.61
   136.5 1606.67   146.3 1608.02     156 1609.86   165.8  1611.4   175.5 1612.71
   185.3 1613.89     195 1614.85   204.8 1615.86   214.5 1617.05   224.3 1618.52
     234 1621.13   243.8 1625.46   253.5 1631.26   263.3  1636.5     273 1640.47
#Mann= 3 , 0 , 0
       0      .1       0   121.8    .045       0   131.8      .1       0
Bank Sta=121.8,131.8
XS Rating Curve= 0 ,0
Exp/Cntr=0.3,0.1

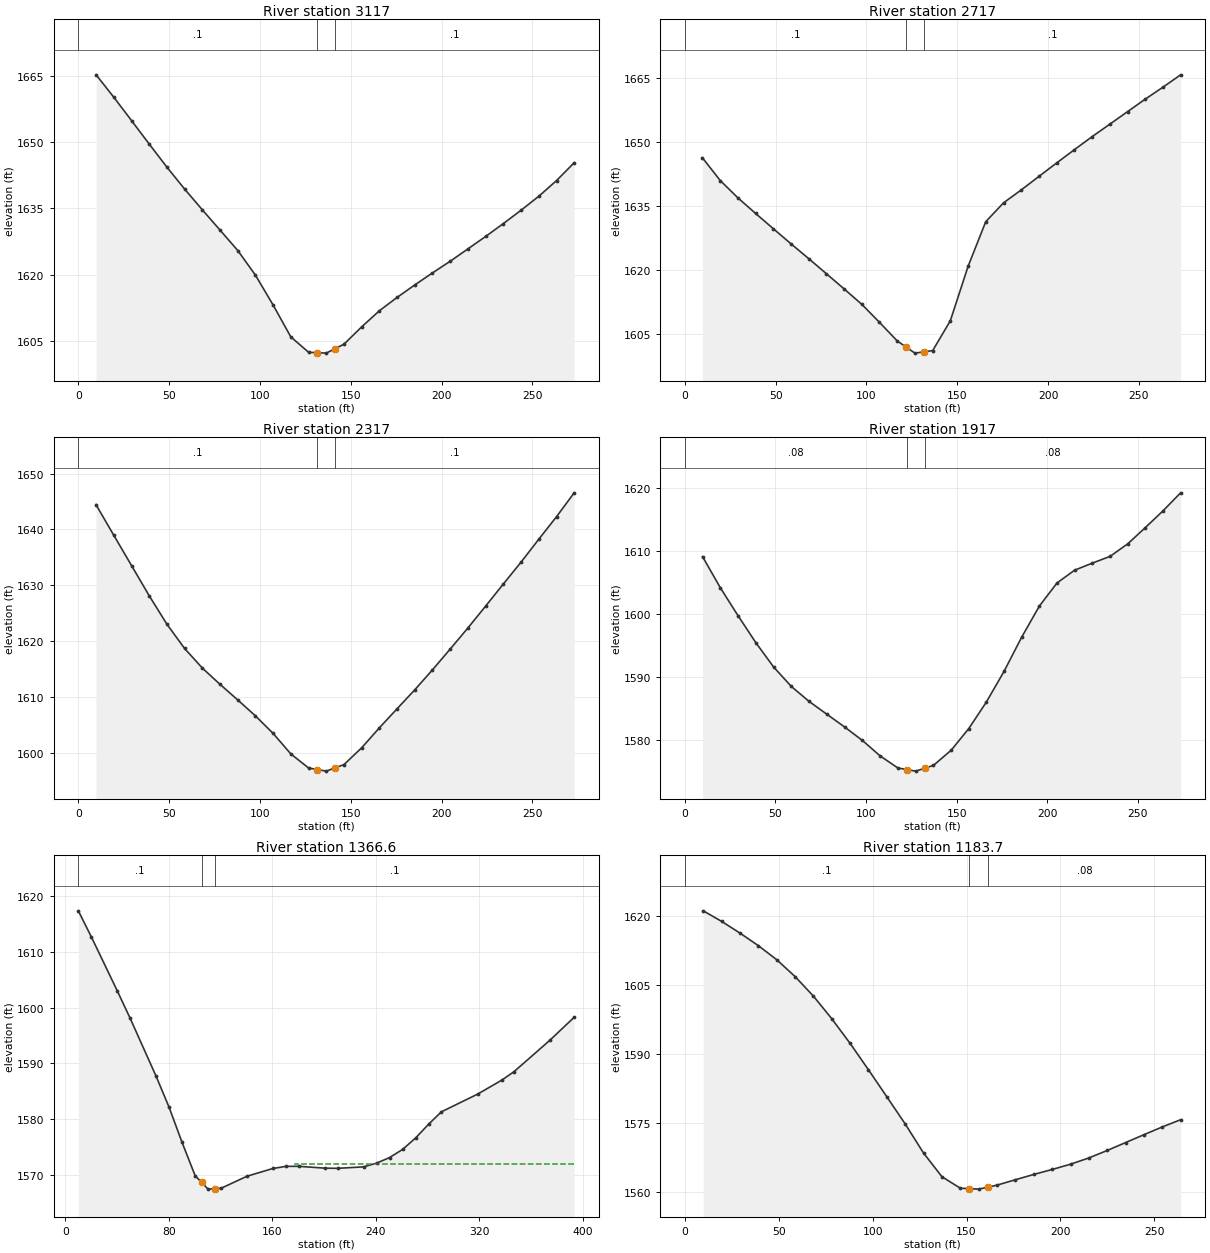
Type RM Length L Ch R = 1 ,3117    ,399.9,400,400.1
XS GIS Cut Line= 3
     1748226.182      109201.714     1748309.633      109093.695
     1748393.085      108985.676
#Sta/Elev= 30
     9.8 1665.18    19.5 1660.13    29.3 1654.83      39 1649.54    48.8 1644.29
    58.5 1639.36    68.3 1634.64      78 1630.08    87.8 1625.45    97.5 1619.89
   107.3 1613.09     117 1605.92   126.8 1602.44   131.5 1602.35   136.5 1602.25
   141.5 1603.29   146.3 1604.28     156 1608.19   165.8 1611.84   175.5 1614.85
   185.3 1617.68     195 1620.39   204.8 1623.04   214.5 1625.82   224.3 1628.64
     234 1631.54   243.7 1634.54   253.5 1637.71   263.3 1641.27     273  1645.3
#Mann= 3 , 0 , 0
       0      .1       0   131.5    .045       0   141.5      .1       0
Bank Sta=131.5,141.5
XS Rating Curve= 0 ,0
Exp/Cntr=0.3,0.1

Type RM Length L Ch R = 1 ,2717    ,399.2,400,400.8
XS GIS Cut Line= 3
     1748538.041      109451.201     1748621.941       109343.53
      1748705.84      109235.859
#Sta/Elev= 30
     9.7  1646.3    19.5 1640.99    29.3 1636.91      39 1633.29    48.8  1629.7
    58.5 1626.18    68.3  1622.7      78 1619.19    87.7 1615.66    97.5 1612.03
   107.2 1607.83     117 1603.48   121.8 1602.08   126.7 1600.64   131.8 1600.95
   136.5 1601.24   146.2 1608.21     156 1620.95   165.7 1631.36   175.5 1635.77
   185.3  1638.8     195 1641.95   204.8 1645.11   214.5 1648.19   224.3 1651.25
     234 1654.15   243.8 1657.09   253.5    1660   263.3 1662.81     273 1665.69
#Mann= 3 , 0 , 0
       0      .1       0   121.8    .045       0   131.8      .1       0
Bank Sta=121.8,131.8
XS Rating Curve= 0 ,0
Exp/Cntr=0.3,0.1

Type RM Length L Ch R = 1 ,2317    ,401.5,400,397.2
XS GIS Cut Line= 3
     1748846.146      109695.645     1748934.459      109591.563
     1749022.771       109487.48
#Sta/Elev= 30
     9.7 1644.43    19.5 1638.95    29.3 1633.51      39 1628.12    48.8    1623
    58.5 1618.67    68.3 1615.15      78 1612.25    87.8 1609.44    97.5  1606.6
   107.3 1603.44     117 1599.78   126.8 1597.26   131.5 1596.99   136.5  1596.7
   141.5  1597.3   146.3 1597.88     156 1600.88   165.8 1604.47   175.5 1607.87
   185.2 1611.25     195 1614.84   204.8 1618.58   214.5 1622.34   224.3 1626.27
     234 1630.21   243.8 1634.14   253.5 1638.22   263.3 1642.27     273 1646.54
#Mann= 3 , 0 , 0
       0      .1       0   131.5    .045       0   141.5      .1       0
Bank Sta=131.5,141.5
XS Rating Curve= 0 ,0
Exp/Cntr=0.3,0.1

Type RM Length L Ch R = 1 ,1917    ,544.6,550.4,557.6
XS GIS Cut Line= 3
     1749179.966      109932.399     1749260.777      109821.479
     1749333.486      109706.159
#Sta/Elev= 30
     9.8 1609.13    19.6 1604.18    29.4 1599.72    39.2 1595.44      49 1591.57
    58.8 1588.47    68.6 1586.09    78.4 1584.05    88.2 1582.02      98 1579.88
   107.8 1577.42   117.6  1575.5   122.4 1575.25   127.4    1575   132.4 1575.46
   137.2 1575.91     147 1578.33   156.7 1581.77   166.4 1585.99   176.2 1590.89
   185.9 1596.32   195.7 1601.28   205.4 1604.94   215.1 1606.97   224.9  1608.1
   234.6 1609.16   244.4 1611.16   254.1 1613.74   263.8 1616.39   273.6 1619.28
#Mann= 3 , 0 , 0
       0     .08       0   122.4    .045       0   132.4     .08       0
Bank Sta=122.4,132.4
XS Rating Curve= 0 ,0
Exp/Cntr=0.3,0.1

Type RM Length L Ch R = 1 ,1366.6  ,191.7,182.9,174.1
XS GIS Cut Line= 3
     1749446.335      110327.366     1749673.705      110146.153
     1749772.342      110174.173
#Sta/Elev= 30
      10 1617.35    20.1 1612.66    40.1 1603.01    50.1 1598.07    70.2 1587.66
    80.2 1582.12    90.2 1575.84   100.3 1569.88   105.3 1568.68   110.3 1567.47
   115.3 1567.55   120.3 1567.62   140.4 1569.78   160.4 1571.17   170.4 1571.55
   180.5 1571.56   200.5 1571.23   210.5  1571.2   230.6 1571.46   240.6 1572.13
   250.6 1573.13   260.7 1574.59   270.7 1576.63   280.7 1579.09   290.7 1581.33
   318.7  1584.5   337.4 1587.01   346.7  1588.5   374.6 1594.17   393.3 1598.27
#Mann= 3 , 0 , 0
      10      .1       0   105.3    .045       0   115.3      .1       0
#XS Ineff= 2 , 0
                          177.85         1571.96
Permanent Ineff=
       F       F
Bank Sta=105.3,115.3
XS Rating Curve= 0 ,0
Exp/Cntr=0.3,0.1

Type RM Length L Ch R = 1 ,1183.7  ,305.6,296.4,287.2
XS GIS Cut Line= 2
     1749619.692      110498.982     1749737.768       110262.83
#Sta/Elev= 29
     9.8 1621.14    19.6 1618.85    29.3 1616.32    39.1 1613.59    48.9 1610.53
    58.7 1606.86    68.5 1602.59    78.2 1597.72      88 1592.34    97.8 1586.59
   107.6  1580.7   117.3 1574.85   127.1 1568.51   136.9 1563.35   146.7 1560.85
   151.5 1560.76   156.5 1560.65   161.5 1561.09   166.2 1561.51     176 1562.69
   185.8 1563.84   195.6 1564.92   205.4 1566.07   215.1 1567.42   224.9 1569.05
   234.7 1570.77   244.5 1572.49   254.2 1574.16     264 1575.74
#Mann= 3 , 0 , 0
       0      .1       0   151.5    .045       0   161.5     .08       0
Bank Sta=151.5,161.5
XS Rating Curve= 0 ,0
Exp/Cntr=0.3,0.1

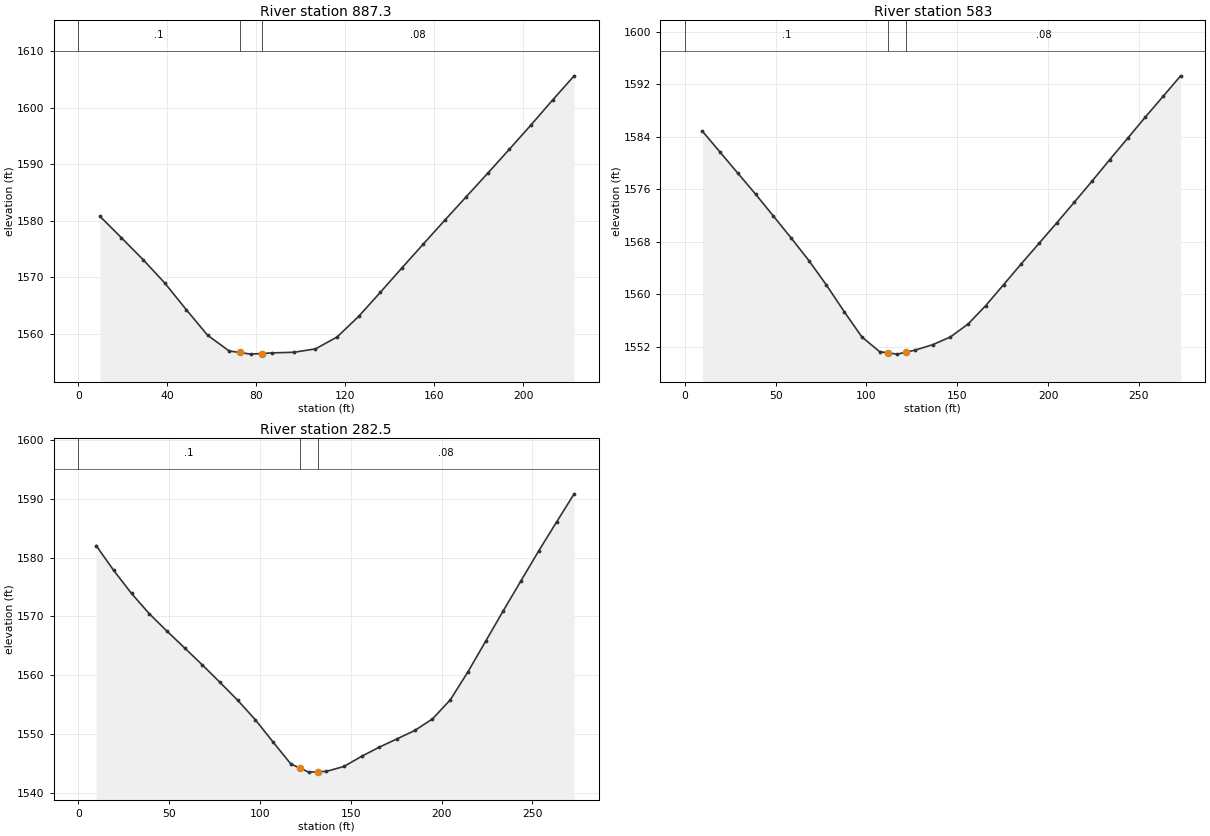
Type RM Length L Ch R = 1 ,887.3   ,304.1,304.3,304.5
XS GIS Cut Line= 2
     1749972.593      110516.229      1749973.92      110293.344
#Sta/Elev= 25
     9.7 1580.82    19.4    1577    29.1 1573.14    38.8 1569.02    48.5 1564.29
    58.1 1559.75    67.8 1556.96    72.5 1556.69    77.5  1556.4    82.5 1556.51
    87.2 1556.62    96.9 1556.73   106.6 1557.33   116.3 1559.43     126 1563.07
   135.7 1567.32   145.4 1571.64   155.1  1575.9   164.7  1580.1   174.4 1584.28
   184.1 1588.46   193.8  1592.7   203.5 1596.99   213.2  1601.4   222.9 1605.69
#Mann= 3 , 0 , 0
       0      .1       0    72.5    .045       0    82.5     .08       0
Bank Sta=72.5,82.5
XS Rating Curve= 0 ,0
Exp/Cntr=0.3,0.1

Type RM Length L Ch R = 1 ,583     ,301.1,300.5,300.4
XS GIS Cut Line= 3
     1750274.742      110556.638     1750276.979      110420.156
     1750279.217      110283.674
#Sta/Elev= 30
     9.7 1584.86    19.5 1581.64    29.2 1578.46      39 1575.25    48.7 1571.95
    58.5  1568.6    68.3 1565.14      78  1561.4    87.8 1557.33    97.5 1553.49
   107.3 1551.24     112 1551.06     117 1550.87     122 1551.18   126.8 1551.48
   136.5 1552.31   146.2 1553.48     156 1555.46   165.7 1558.27   175.5 1561.45
   185.2 1564.62     195 1567.75   204.8 1570.88   214.5 1574.04   224.3 1577.27
     234 1580.53   243.8 1583.77   253.5 1586.99   263.3 1590.15     273  1593.3
#Mann= 3 , 0 , 0
       0      .1       0     112    .045       0     122     .08       0
Bank Sta=112,122
XS Rating Curve= 0 ,0
Exp/Cntr=0.3,0.1

Type RM Length L Ch R = 1 ,282.5   ,269.5,282.5,295
XS GIS Cut Line= 3
      1750578.01      110590.547     1750576.503      110454.006
     1750578.328      110317.527
#Sta/Elev= 30
     9.8 1582.04    19.5  1577.8    29.3 1573.89      39 1570.47    48.8 1567.49
    58.5 1564.64    68.3 1561.74      78 1558.78    87.8 1555.72    97.5 1552.41
   107.3 1548.61     117 1544.91   121.8 1544.23   126.8 1543.52   131.8 1543.58
   136.5 1543.64   146.3 1544.49     156 1546.21   165.8 1547.78   175.5 1549.18
   185.3 1550.61     195 1552.57   204.8 1555.81   214.5 1560.56   224.3 1565.79
     234 1570.96   243.8 1576.09   253.5 1581.14   263.3 1586.03     273 1590.83
#Mann= 3 , 0 , 0
       0      .1       0   121.8    .045       0   131.8     .08       0
Bank Sta=121.8,131.8
XS Rating Curve= 0 ,0
Exp/Cntr=0.3,0.1

Chan Stop Cuts=-1
Use User Specified Reach Order=0